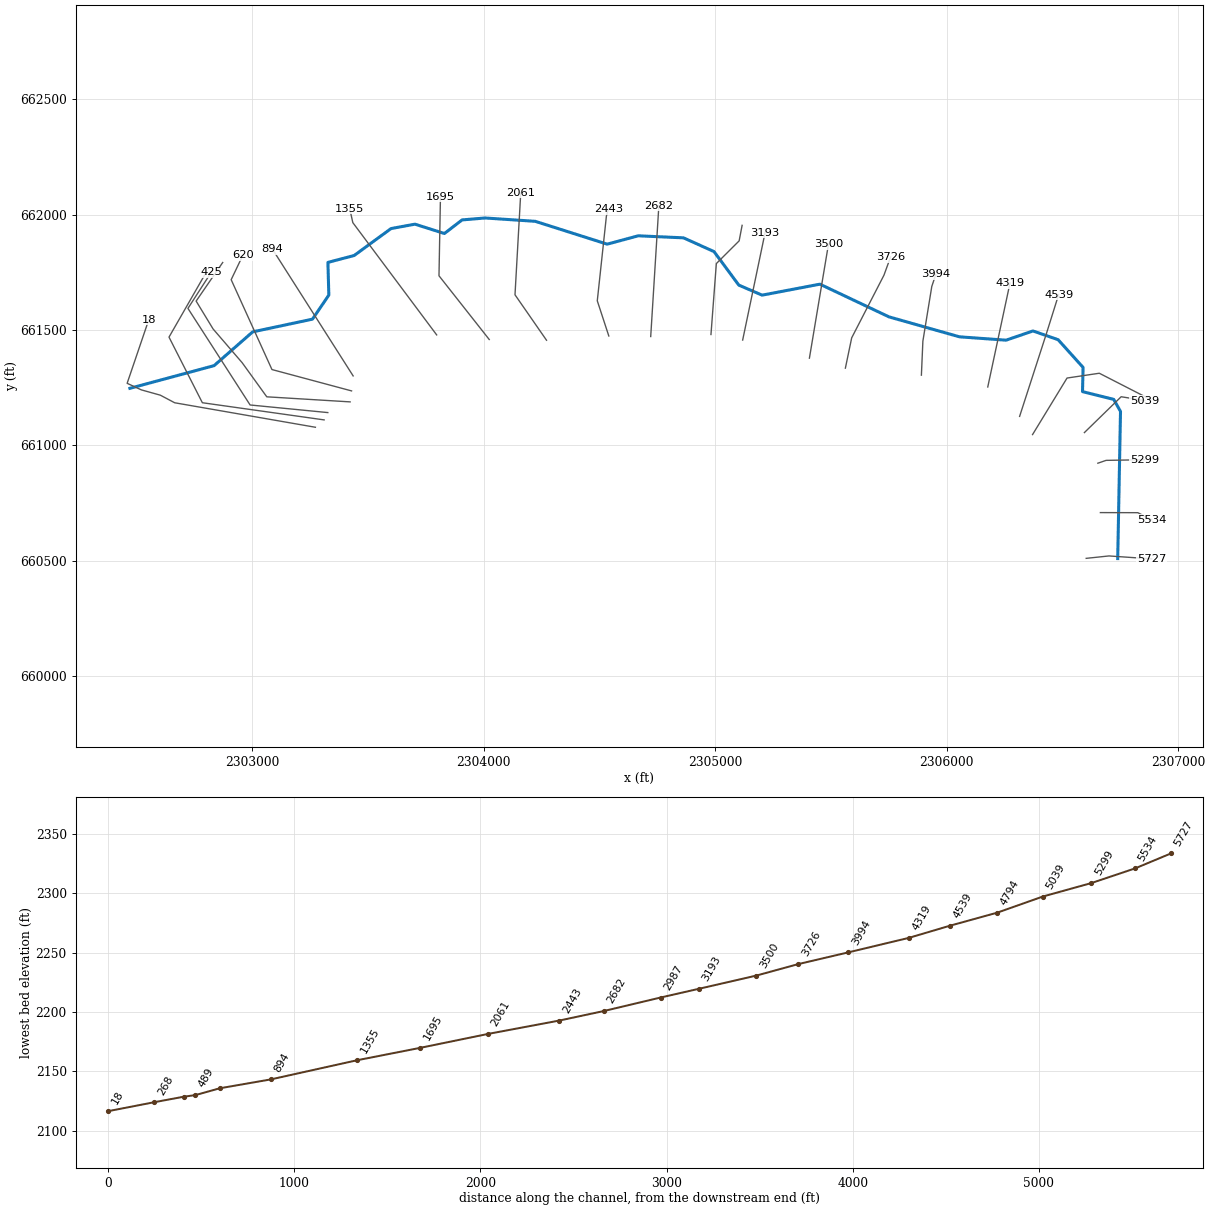
--- LIMEKNRN2.prj (project) ---

Proj Title=LIMEKNRN2
Current Plan=p01
Default Exp/Contr=0,0
English Units
Geom File=g01
Flow File=f01
Plan File=p01
BEGIN DESCRIPTION:
----------MODEL BY WOOD PLC 2022----------
AFH study
Randolph County, WV
HEC-RAS Version: RAS 6.2
Vertical Datum: NAVD88
Projection: NAD 1983 StatePlane West Virginia S FIPS 4702 (US Feet)
Terrain: 1-meter LIDAR (FEMA Region III 3DEP collected 2016-2018)
Land Use: 2019 NLCD
Hydrologic Method:
WV SIR2010-5033 regression equations
Additional Model Notes:
None
END DESCRIPTION:
DSS Export Rating Curves= 0
DSS Export Rating Curve Sorted= 0
DSS Export Volume Flow Curves= 0
DXF Filename=..\LIMEKNRN2.
DXF OffsetX= 0
DXF OffsetY= 0
DXF ScaleX= 0
DXF ScaleY= 0

--- LIMEKNRN2.p01 (plan) ---

Plan Title=Floodplain
Program Version=6.20
Short Identifier=Floodplain
Geom File=g01
Flow File=f01
Subcritical Flow
K Sum by GR= 0
Std Step Tol= 0.01
Critical Tol= 0.01
Num of Std Step Trials= 20
Max Error Tol= 0.3
Flow Tol Ratio= 0.001
Split Flow NTrial= 30
Split Flow Tol= 0.02
Split Flow Ratio= 0.02
Log Output Level= 0
Friction Slope Method= 1
Unsteady Friction Slope Method= 2
Unsteady Bridges Friction Slope Method= 1
Parabolic Critical Depth
Global Vel Dist= 0 , 0 , 0
Global Log Level= 0
CheckData=True
Encroach Param=-1 ,0,0, 0
Mapping Interval=1HOUR
Computation Time Step Use Courant=        0
Computation Time Step Use Time Series=    0
Computation Time Step Count To Double=0
Computation Time Step Max Doubling=0
Computation Time Step Max Halving=0
Computation Time Step Residence Courant=0
Run HTab= 0
Run UNet= 0
Run Sediment= 0
Run PostProcess= 0
Run WQNet= 0
Run RASMapper=-1
UNET Theta= 0
UNET Theta Warmup= 0
UNET ZTol= 0
UNET ZSATol= 0
UNET MxIter= 0
UNET Max Iter WO Improvement= 0
UNET MaxInSteps= 0
UNET DtIC= 0
UNET DtMin= 0
UNET MaxCRTS= 0
UNET WFStab= 0
UNET SFStab= 0
UNET WFX= 1
UNET SFX= 1
UNET Gravity=32.174
UNET 1D Methodology=Finite Difference
UNET DSS MLevel= 1
UNET Pardiso=0
UNET DZMax Abort= 0
UNET Use Existing IB Tables= 0
UNET Froude Reduction=False
UNET Froude Limit= 0
UNET Froude Power= 0
UNET D1 Cores= 0
UNET WindReference=Eulerian
UNET WindDragFormulation=Hsu (1988)
UNET D2 Coriolis=0
UNET D2 Cores= 0
UNET D2 Theta= 1
UNET D2 Theta Warmup= 1
UNET D2 Z Tol= 0.01
UNET D2 Volume Tol= 0.01
UNET D2 Max Iterations= 20
UNET D2 Equation= 0
UNET D2 RampUpFraction=0.1
UNET D2 TimeSlices= 1
UNET D2 Turbulence Formulation=Non-Conservative (original)
UNET D2 Eddy Viscosity=0.3
UNET D2 Transverse Eddy Viscosity=0.1
UNET D2 Smagorinsky Mixing=0
UNET D2 BCVolumeCheck=0
UNET D2 Cores=0
UNET D2 SolverType=PARDISO (Direct)
UNET D2 Minimum Iterations= 2147483647
UNET D2 Maximum Iterations= 2147483647
UNET D2 Restart Number= 10
UNET D2 Relaxation Coeff=1.3
UNET D2 SOR Precondition Iterations= 10
UNET D2 ILUT Maximum Fill= 8
UNET D2 ILUT Tolerance=1E-08
UNET D1D2 MaxIter= 0
UNET D1D2 ZTol=0.01
UNET D1D2 QTol=0.1
UNET D1D2 MinQTol=1
Write IC File= 0
Write IC File at Fixed DateTime=0
Write IC File at Sim End=0
Echo Input=False
Echo Parameters=False
Echo Output=False
Write Detailed= 0
HDF Write Warmup=0
HDF Write Time Slices=0
HDF Flush=0
HDF Compression= 1
HDF Chunk Size= 1
HDF Spatial Parts= 1
HDF Use Max Rows=0
HDF Fixed Rows= 1
Calibration Method= 0
Calibration Iterations= 20
Calibration Max Change=0.05
Calibration Tolerance=0.2
Calibration Maximum=1.5
Calibration Minimum=0.5
Calibration Optimization Method= 1
WQ AD Non Conservative
WQ ULTIMATE=-1
WQ Max Comp Step=1HOUR
WQ Output Interval=15MIN
WQ Output Selected Increments= 0
WQ Output face flow=0
WQ Output face velocity=0
WQ Output face area=0
WQ Output face dispersion=0
WQ Output cell volume=0
WQ Output cell surface area=0
WQ Output cell continuity=0
WQ Output cumulative cell continuity=0
WQ Output face conc=0
WQ Output face dconc_dx=0
WQ Output face courant=0
WQ Output face peclet=0
WQ Output face adv mass=0
WQ Output face disp mass=0
WQ Output cell mass=0
WQ Output cell source sink temp=0
WQ Output nsm pathways=0
WQ Output nsm derived pathways=0
WQ Create Restart=0
WQ Fixed Restart=0
WQ System Summary=0
WQ Write To DSS=0
Sorting and Armoring Iterations= 10
XS Update Threshold= 0.02
Bed Roughness Predictor= 0
Hydraulics Update Threshold= 0.02
Energy Slope Method= 1
Volume Change Method= 1
Sediment Retention Method= 0
Sediment TS Multiplier= 1
Warm Up Method= 0
XS Weighting Method= 0
Number of US Weighted Cross Sections= 1
Number of DS Weighted Cross Sections= 1
Upstream XS Weight=0
Main XS Weight=1
Downstream XS Weight=0
Number of DS XS's Weighted with US Boundary= 1
Upstream Boundary Weight= 1
Weight of XSs Associated with US Boundary= 0
Number of US XS's Weighted with DS Boundary= 1
Downstream Boundary Weight= 0.5
Weight of XSs Associated with DS Boundary= 0.5
Percentile Method= 0
Sediment Output Level= 3
Mass or Volume Output= 0
Output Increment Type= 1
Profile and TS Output Increment= 1
Transport Output Increment 1
XS Output Flag= 0
XS Output Increment= 10
Read HDF5 Sediment Hotstart= 0
Sediment Hotstart Type= 0
Write Gradation File= 0
Read Gradation Hotstart= 0
Write HDF5 File= 1
Write Binary Output= 1
Write DSS Sediment File= 0
DSS Sediment Output Type= 1
SV Curve= 0
Specific Gage Flag= 0
Subcell Erosion Methods= 0
Subcell Deposition Methods= 0
Advection Scheme= 1
Matrix Solver= 0
Implicit Weighting Factor= 1
Maximum Outer Loop Convergence Iterations= 5
Convergence Maximum Absolute= 0.001
Convergence RMSE= 0.0001
Grain Fractions Max Abs Error= 0.001
Max Subgrid Regions= 1
Max Subgrid Length Scale= 3.402823E+38
Initial Layer Thickness= 3.402823E+38
Min Layer Thickness= 3.402823E+38
Max Layer Thickness= 3.402823E+38
Number of Layers= 5

--- LIMEKNRN2.f01 (steady flow) ---

Flow Title=Flow
Program Version=6.20
Number of Profiles= 1
Profile Names=P100yr
River Rch & RM=LIMEKNRN2,Main,5727
     343
River Rch & RM=LIMEKNRN2,Main,268
     585
Boundary for River Rch & Prof#=LIMEKNRN2,Main            , 1
Up Type= 0
Dn Type= 3
Dn Slope=0.02915
DSS Import GetInterval= 0
DSS Import GetPeak= 0
DSS Import FillOption= 0

--- LIMEKNRN2.g01 (geometry) ---

Geom Title=Geometry
Program Version=6.20

River Reach=LIMEKNRN2       ,Main
Reach XY= 30
2306738.94711241660508.5958933942306751.00376845661146.798237815
2306721.53126324661198.964572048 2306586.8419144661232.563227995
2306589.29900001661337.5380000172306481.45299999661457.773000002
2306372.85100001661495.6239999982306256.54700001661455.640000016
2306055.24200001661470.2000000032305750.66300002661556.709000006
2305452.26600005661698.4909999972305202.54261436661650.857200143
 2305101.7719715661694.5149715152304994.88200003661839.669000015
2304862.91199999661899.3819999992304667.32835719661908.221185564
2304533.15872716661871.9708862172304222.65000001661970.953000009
2304005.54099999661985.481000006     2303906.325661977.107999995
2303829.91012854661918.205714392     2303702.671661958.650000006
     2303599.315661939.6110000162303439.98900004661822.789000005
2303326.57300001661792.9360000042303330.55315707 661651.12371439
2303259.87641419661546.7490715872303001.52200001      661491.647
2302834.79000001661345.2109999952302471.02735399 661246.88612554

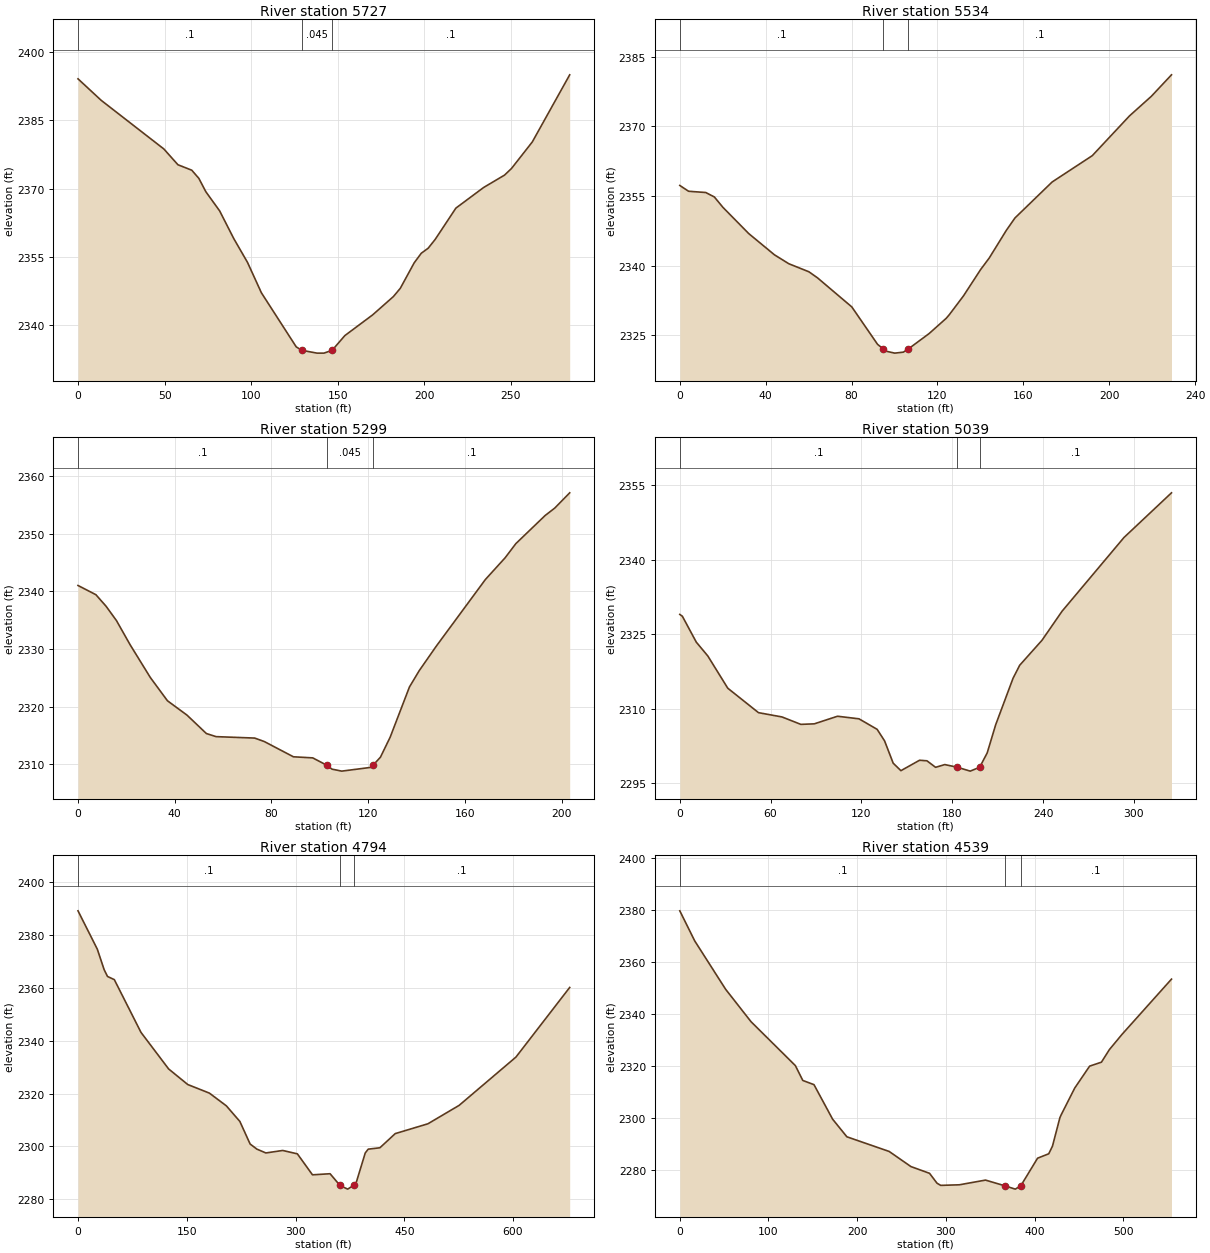
Type RM Length L Ch R = 1 ,5727    ,192.5,192.7,192.8
XS GIS Cut Line= 3
2306602.80448399660509.609719606 2306701.3605492660520.045067687
2306885.71836531660507.290753365
#Sta/Elev= 30
       0 2394.11    13.4 2389.38    49.6 2378.68    57.7 2375.22    65.7 2374.02
    69.8 2372.22    73.8  2369.3    81.8 2365.07    89.9 2359.02    97.9 2353.74
   105.9 2347.07     126 2335.19   129.2 2334.43     138 2333.81     142 2333.81
  146.73 2334.43   154.1 2337.67   170.1 2342.21   182.1 2346.24   186.1 2348.06
   194.1 2353.65   198.2 2355.76   202.2 2356.88   206.2 2358.79   218.2 2365.69
   234.2 2370.22   246.3 2372.95   250.3  2374.4   262.3 2380.23283.9055 2394.99
#Mann= 3, -1 ,  0
       0     0.1       0   129.2   0.045       0  146.73     0.1       0
Bank Sta=129.2,146.73
XS Rating Curve= 0 ,0
Exp/Cntr(USF)=0,0
Exp/Cntr=0.3,0.1

Type RM Length L Ch R = 1 ,5534    ,234.3,235.2,235.1
XS GIS Cut Line= 3
 2306664.0500973660708.0199713882306825.76480357660707.615684622
2306885.59924488660676.889890432
#Sta/Elev= 30
       0 2357.28     4.1 2356.03    12.1 2355.76    16.1  2354.8    20.1 2352.56
    32.1 2346.92    44.1 2342.34    50.8 2340.42    60.1  2338.7    64.1  2337.4
    80.1 2331.13    92.1 2323.07    94.7  2322.1    96.1 2321.59   100.1 2321.18
   104.1 2321.39  106.45 2322.09   116.1 2325.39   124.1 2328.69   125.6 2329.51
   132.1  2333.5   140.1 2339.18   144.1 2341.66   152.1 2347.64   156.1 2350.29
   173.4 2358.03   192.1  2363.7   209.4 2372.25   219.6 2376.48228.9776  2381.1
#Mann= 3, -1 ,  0
       0     0.1       0    94.7   0.045       0  106.45     0.1       0
Bank Sta=94.7,106.45
XS Rating Curve= 0 ,0
Exp/Cntr(USF)=0,0
Exp/Cntr=0.3,0.1

Type RM Length L Ch R = 1 ,5299    ,252.6,260.1,264.1
XS GIS Cut Line= 3
2306653.18152108660922.1567704422306688.78400683660934.480707819
2306854.47249824660937.219360569
#Sta/Elev= 30
       0 2341.02     7.4 2339.42    11.6 2337.42    15.9 2334.93    21.5 2330.77
    29.9 2325.05      37    2321    45.1  2318.5    53.1 2315.31    57.1 2314.77
    73.1 2314.52    77.1 2313.91    89.1 2311.27    97.1 2311.08  102.88 2309.81
   105.1 2309.12   109.1 2308.78   121.1 2309.43  122.01 2309.79   125.1  2311.2
   129.1 2314.65   137.1 2323.39   141.1  2326.2   148.2 2330.48   168.5 2342.05
   176.7 2345.84   181.1 2348.28   193.2 2353.16   197.2 2354.46203.3863 2357.11
#Mann= 3, -1 ,  0
       0     0.1       0  102.88   0.045       0  122.01     0.1       0
Bank Sta=102.88,122.01
XS Rating Curve= 0 ,0
Exp/Cntr(USF)=0,0
Exp/Cntr=0.3,0.1

Type RM Length L Ch R = 1 ,5039    ,246.9,244.7,235.3
XS GIS Cut Line= 3
2306594.98515013661054.9814288412306753.82700966661210.399972432
2306855.15716142661193.968055929
#Sta/Elev= 30
       0 2329.02     1.7 2328.65    10.9 2323.43    18.5 2320.65    31.7 2314.15
      52 2309.22    67.5 2308.36      80 2306.86    88.9 2306.97   104.2  2308.5
   118.4 2307.98   130.4 2305.86   135.3 2303.54     141 2299.04   146.1 2297.53
   158.4 2299.63   163.3 2299.52     169 2298.21   175.1 2298.76   183.4 2298.22
   191.9 2297.44  198.12 2298.22   203.1  2301.1   208.7 2306.77   220.2 2316.16
   224.6 2318.78   239.3  2323.8   252.6 2329.67   293.5 2344.52324.8827 2353.52
#Mann= 3, -1 ,  0
       0     0.1       0   183.4   0.045       0  198.12     0.1       0
Bank Sta=183.4,198.12
XS Rating Curve= 0 ,0
Exp/Cntr(USF)=0,0
Exp/Cntr=0.3,0.1

Type RM Length L Ch R = 1 ,4794    ,244.1,255.9,264.6
XS GIS Cut Line= 4
2306371.02177595661046.3347130122306520.01273238661291.448867144
2306659.39136905661312.2755599792306882.07677705661197.728749388
#Sta/Elev= 30
       0 2389.24    26.7 2374.68    36.1 2366.93    40.7 2364.39    50.1 2363.18
    86.9  2343.2     125 2329.36   151.4 2323.45   181.2 2320.21   204.6 2315.39
   223.3 2309.46   237.4 2300.93   246.7    2299   259.1 2297.54   282.4 2298.48
   302.6  2297.2   323.4 2289.26   347.7 2289.67  361.412285.219   371.9 2283.84
   380.1 2285.24   384.1 2286.64   396.2 2297.54   400.3 2298.98   416.4  2299.5
   437.6 2304.87   482.6 2308.58   525.7 2315.56   604.1 2333.86   678.2 2360.22
#Mann= 3, -1 ,  0
       0     0.1       0  361.41   0.045       0   380.1     0.1       0
Bank Sta=361.41,380.1
XS Rating Curve= 0 ,0
Exp/Cntr(USF)=0,0
Exp/Cntr=0.3,0.1

Type RM Length L Ch R = 1 ,4539    ,215.4,219.7,218.9
XS GIS Cut Line= 3
2306315.07051653661125.1595847142306431.21137015661485.261114094
2306483.76672849661653.308494471
#Sta/Elev= 30
       0 2379.58    16.8 2368.05    51.7 2349.45    80.3 2337.02   130.3 2320.16
   138.7 2314.45   151.3 2312.84   172.3 2299.59   188.4 2292.82   236.1 2287.19
   260.6 2281.39   281.6  2278.8     290 2275.01   294.2 2274.17   315.2 2274.39
   344.7  2276.2   366.4 2274.01   378.3 2272.73  384.582274.066   403.4 2284.61
     416  2286.3   420.2 2289.23   428.6  2300.2   430.2 2301.39   445.3 2311.54
   462.1 2319.95   475.4 2321.47   484.4 2326.31   498.7 2332.18   554.4 2353.36
#Mann= 3, -1 ,  0
       0     0.1       0   366.4   0.045       0  384.58     0.1       0
Bank Sta=366.4,384.58
XS Rating Curve= 0 ,0
Exp/Cntr(USF)=0,0
Exp/Cntr=0.3,0.1

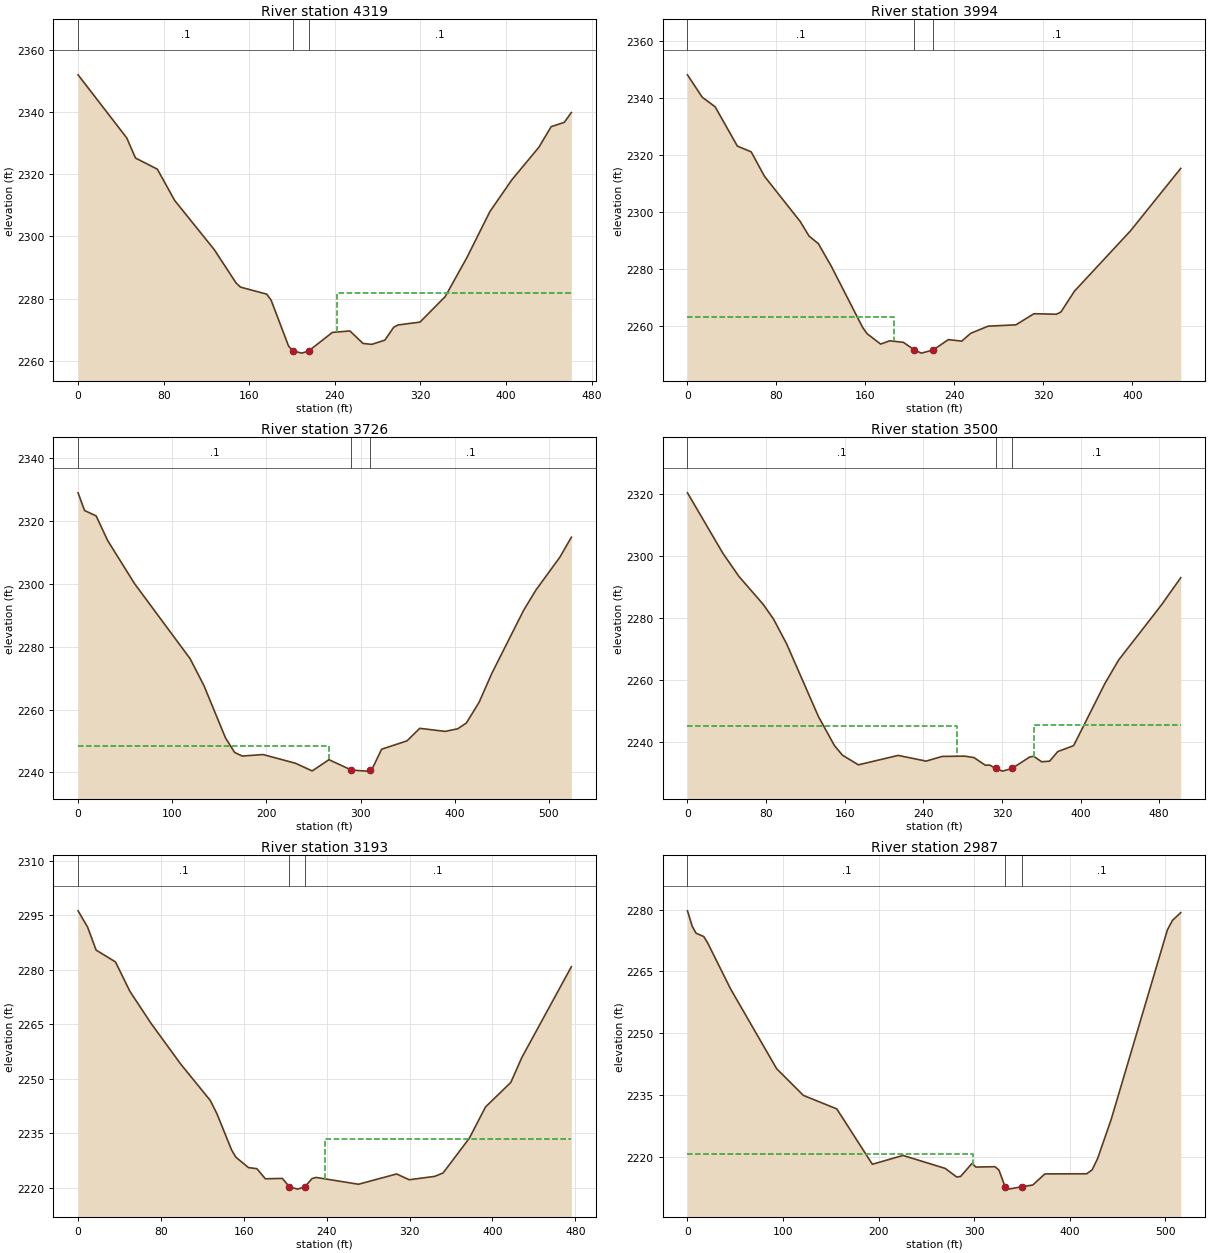
Type RM Length L Ch R = 1 ,4319    ,324.3,324.9,324.7
XS GIS Cut Line= 2
2306177.50173456661252.6910292642306273.62493226661703.669031802
#Sta/Elev= 30
       0 2351.93    45.5 2331.66    53.7 2325.19    74.1 2321.62    90.3 2311.57
   127.3 2295.77   147.7 2285.05   151.8 2283.73   176.4 2281.46   180.5  2279.5
   196.8 2264.76   200.9 2263.23   209.1 2262.52   215.5  2263.2   237.7 2269.17
   254.1 2269.65   266.3 2265.64   274.5 2265.33   286.8  2266.7     295 2270.82
   299.1 2271.57   319.6 2272.48   343.2 2280.69   363.4 2293.18   384.9 2307.96
   405.4 2318.16   430.8 2328.69   442.2 2335.27   454.5 2336.66   461.1 2339.81
#Mann= 3, -1 ,  0
       0     0.1       0   200.9   0.045       0   215.5     0.1       0
#XS Ineff= 2 , 0
                          241.66         2281.73
Permanent Ineff=
       F       F
Bank Sta=200.9,215.5
XS Rating Curve= 0 ,0
Exp/Cntr(USF)=0,0
Exp/Cntr=0.3,0.1

Type RM Length L Ch R = 1 ,3994    ,269.4,268.1,263.3
XS GIS Cut Line= 4
2305890.73419476661303.9567347032305897.14240794661451.345637842
2305935.59168701  661688.44952552305953.21427326661741.317284234
#Sta/Elev= 30
       0 2348.18    13.2 2340.33    24.9 2336.93    44.8 2323.14    57.3 2321.08
    69.3 2312.45   101.3 2296.63   109.3 2291.47   117.7 2288.79   129.3 2280.87
   157.5 2259.32   161.5 2257.13   173.7 2253.48   181.8 2254.63     194 2254.11
   204.1 2251.43   204.1 2251.41   210.2  2250.3  220.852251.391   234.5 2255.04
   246.6 2254.53   254.7 2257.28   270.3 2259.78   295.3 2260.25   311.5 2264.16
   331.7 2263.98   335.8 2264.78   347.9 2272.08   398.3 2293.31   443.5 2315.28
#Mann= 3, -1 ,  0
       0     0.1       0   204.1   0.045       0  220.85     0.1       0
#XS Ineff= 2 , 0
          185.42 2262.91
Permanent Ineff=
       F       F
Bank Sta=204.1,220.85
XS Rating Curve= 0 ,0
Exp/Cntr(USF)=0,0
Exp/Cntr=0.3,0.1

Type RM Length L Ch R = 1 ,3726    ,222,225.7,227.4
XS GIS Cut Line= 4
2305562.31326928661334.395747308 2305589.5481753661465.764117497
2305728.92681196661737.3121509972305757.76377127661816.613789099
#Sta/Elev= 30
       0 2328.87     6.9 2323.25    19.2 2321.53    31.4 2313.72      60    2300
     119 2276.15   133.6 2267.65   156.5 2251.02   166.2 2246.38   174.3 2245.22
   196.4  2245.7   230.8 2242.94   248.6 2240.49   266.4 2244.07   290.2 2240.77
   306.3 2240.43  310.292240.818   313.3 2241.75   322.3 2247.39   349.3 2250.05
   362.8 2254.03   389.8 2253.06   403.1 2253.88   412.3 2255.72   425.8 2262.28
   439.2  2271.4     473 2291.47   486.1 2297.94   511.6 2308.41   523.8 2314.76
#Mann= 3, -1 ,  0
       0     0.1       0   290.2   0.045       0  310.29     0.1       0
#XS Ineff= 2 , 0
          266.59 2248.29
Permanent Ineff=
       F       F
Bank Sta=290.2,310.29
XS Rating Curve= 0 ,0
Exp/Cntr(USF)=0,0
Exp/Cntr=0.3,0.1

Type RM Length L Ch R = 1 ,3500    ,306.4,307.5,306.4
XS GIS Cut Line= 2
2305406.91409967661377.6511862732305489.41984436661872.685654423
#Sta/Elev= 30
       0 2320.45      36 2300.97    52.2 2293.56    77.2 2284.43    87.6 2279.72
   100.9 2271.74   133.3 2248.28   149.6 2238.92   157.7 2235.85   173.9 2232.74
   214.4 2235.78   242.8 2233.94   259.1 2235.45   282.2 2235.54   291.5 2235.08
   303.1 2232.61   307.7 2232.65   313.5 2231.58   320.5 2230.71  330.182231.569
   348.3 2235.28   352.3 2235.49   360.4 2233.73   368.5 2233.92   376.7    2237
   392.9 2238.93   424.7 2258.95   438.6 2266.49   482.1 2284.23   501.9 2293.08
#Mann= 3, -1 ,  0
       0     0.1       0   313.5   0.045       0  330.18     0.1       0
#XS Ineff= 2 ,-1
       0  274.39 2245.18  352.74501.8629 2245.48
Permanent Ineff=
       F       F
Bank Sta=313.5,330.18
XS Rating Curve= 0 ,0
Exp/Cntr(USF)=0,0
Exp/Cntr=0.3,0.1

Type RM Length L Ch R = 1 ,3193    ,210.1,206.1,201.7
XS GIS Cut Line= 2
2305118.54450657661456.1517977272305215.46873092661922.349306568
#Sta/Elev= 30
       0 2296.16     9.2 2291.68    17.4 2285.36    36.1 2282.11    50.1 2273.98
    70.5 2265.18    99.1    2254   127.7 2243.97   134.2 2240.24   148.1 2230.44
   152.2 2228.42   164.5 2225.52   172.6 2225.23   180.8 2222.44   197.2 2222.55
  204.052220.225     212  2219.6  218.992220.235   225.8 2222.49   229.8 2222.82
   270.7 2220.94   307.5 2223.77   319.7 2222.18   344.2  2223.1   352.4 2224.05
   377.7  2233.6   393.3 2242.19   417.8 2248.97   428.4 2255.81   476.2 2280.77
#Mann= 3, -1 ,  0
       0     0.1       0  204.05   0.045       0  218.99     0.1       0
#XS Ineff= 1 ,-1
  237.99476.1664 2233.42
Permanent Ineff=
       F
Bank Sta=204.05,218.99
XS Rating Curve= 0 ,0
Exp/Cntr(USF)=0,0
Exp/Cntr=0.3,0.1

Type RM Length L Ch R = 1 ,2987    ,299.2,305.1,311.1
XS GIS Cut Line= 4
2304981.56894985661480.1825971522305004.79872263661787.776829789
2305103.32500027 661886.303107432305116.14142663 661953.58934582
#Sta/Elev= 30
       0  2279.7       5 2275.94       9 2274.27      17 2273.47    21.1 2271.94
    45.1 2260.77    93.3 2241.43   121.3 2234.95   156.3 2231.67   193.5 2218.25
   225.6 2220.39   269.8 2217.24   281.8 2215.16   285.8 2215.28   297.8 2218.45
   301.9 2217.57   321.8 2217.66     326 2216.84  332.542212.754   335.9 2212.22
   350.1  2212.8   361.4 2213.22   374.1 2215.91   417.9 2215.94   423.6 2216.91
   429.2  2219.6   443.4 2229.06   502.3 2275.07   507.7  2277.4   516.3 2279.27
#Mann= 3, -1 ,  0
       0     0.1       0  332.54   0.045       0   350.1     0.1       0
#XS Ineff= 2 , 0
          299.15 2220.64
Permanent Ineff=
       F       F
Bank Sta=332.54,350.1
XS Rating Curve= 0 ,0
Exp/Cntr(USF)=0,0
Exp/Cntr=0.3,0.1

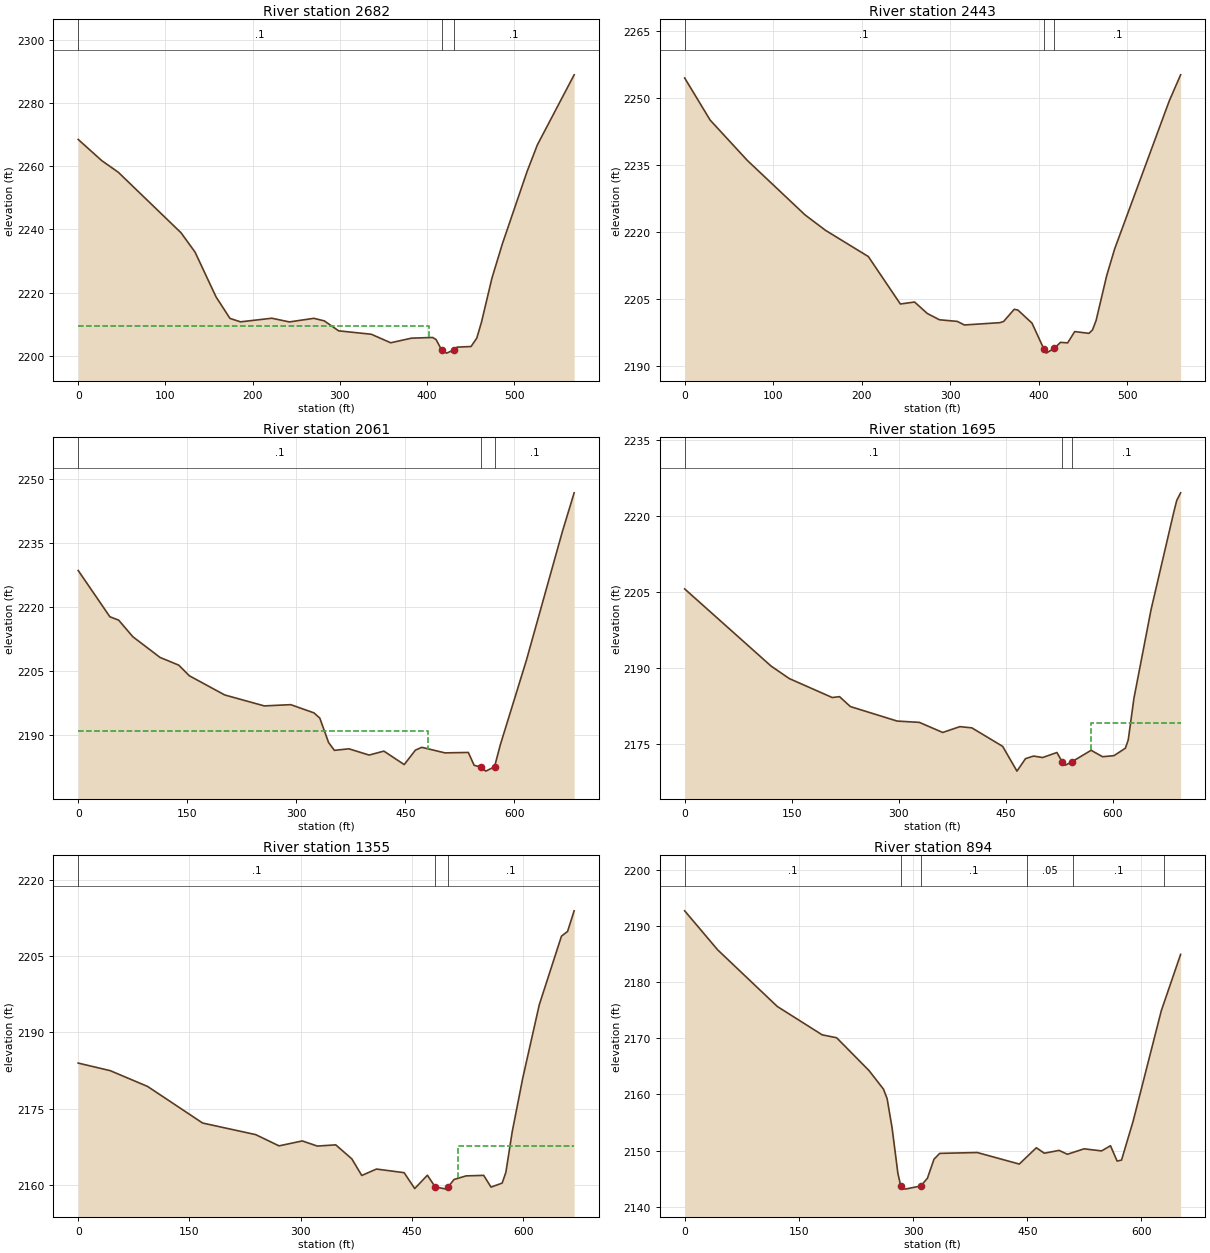
Type RM Length L Ch R = 1 ,2682    ,236.5,238.4,236.4
XS GIS Cut Line= 2
2304721.23528942661471.3713040292304756.48046191662039.299197102
#Sta/Elev= 30
       0 2268.48    27.1 2261.76    45.9 2258.12     118 2238.93   134.1 2232.79
   158.1 2218.65   174.1 2211.82   186.2 2210.73   222.2 2211.87   242.3  2210.7
   270.3 2211.84   282.3 2211.04   298.8 2207.88   336.3  2206.8   358.5  2204.1
   382.5 2205.56   406.6 2205.78   410.6 2205.12  416.962201.811   422.6 2200.82
   430.9 2201.81   434.7 2202.72   450.7 2202.91   457.3 2205.58   462.7 2210.65
   474.7 2224.59   486.7 2235.47   514.8 2258.19   526.8 2266.77     569 2288.95
#Mann= 3, -1 ,  0
       0     0.1       0  416.96   0.045       0   430.9     0.1       0
#XS Ineff= 2 , 0
           402.6 2209.55
Permanent Ineff=
       F       F
Bank Sta=416.96,430.9
XS Rating Curve= 0 ,0
Exp/Cntr(USF)=0,0
Exp/Cntr=0.3,0.1

Type RM Length L Ch R = 1 ,2443    ,380.3,382.1,382.6
XS GIS Cut Line= 4
2304540.20326708661473.7743839722304490.41031789661626.425869008
2304529.78992067661993.6406781942304537.80018714662023.278664152
#Sta/Elev= 30
       0 2254.56    28.8 2245.11    70.9 2236.04     136 2223.84   159.3 2220.35
   207.6 2214.48   243.8 2203.83   259.9 2204.27   274.3 2201.69     288 2200.29
   308.2 2199.92   316.2 2199.12   356.4 2199.64   360.5 2199.91   372.5 2202.64
   376.6 2202.48   392.6 2199.54405.76532193.836   408.7  2192.8418.00152193.913
   424.8 2195.22   432.9  2195.1   440.9 2197.64     457 2197.24     461 2198.02
   465.1 2200.15   477.1 2210.25   486.1 2216.23   547.8 2249.44   560.6 2255.27
#Mann= 3, -1 ,  0
       0     0.1       0405.7653   0.045       0418.0015     0.1       0
Bank Sta=405.7653,418.0015
XS Rating Curve= 0 ,0
Exp/Cntr(USF)=0,0
Exp/Cntr=0.3,0.1

Type RM Length L Ch R = 1 ,2061    ,364.3,365.8,365.8
XS GIS Cut Line= 3
2304271.05831353661455.3507710792304134.88378345661652.403326363
2304159.71560952662094.570035778
#Sta/Elev= 30
       0 2228.48    43.6 2217.65    55.7 2216.86    75.2 2212.98   112.6 2208.14
   138.4 2206.33   152.9 2203.85   201.6 2199.36     256  2196.8   292.4 2197.09
   324.4 2195.17   332.4 2193.95   344.5 2188.24   352.5  2186.4   372.5 2186.76
   400.3  2185.3   420.6 2186.22   448.6 2183.07   463.9 2186.44   472.7 2187.11
   504.7 2185.81   536.8 2185.91   544.8  2182.9  554.142182.501   560.8 2181.54
   572.8 2182.54   580.8 2187.69   616.8 2207.54   666.3 2237.64   682.4 2246.65
#Mann= 3, -1 ,  0
       0     0.1       0  554.14   0.045       0   572.8     0.1       0
#XS Ineff= 2 , 0
          481.18 2190.99
Permanent Ineff=
       F       F
Bank Sta=554.14,572.8
XS Rating Curve= 0 ,0
Exp/Cntr(USF)=0,0
Exp/Cntr=0.3,0.1

Type RM Length L Ch R = 1 ,1695    ,331.4,339.8,342.4
XS GIS Cut Line= 3
2304023.54107945661458.5548776692303806.46285798661734.909071054
2303812.87107116662078.549502829
#Sta/Elev= 30
       0 2205.66   121.1 2190.45   146.7 2187.98   206.8 2184.25     217 2184.42
   232.2 2182.47   297.7 2179.61   328.9 2179.35   361.7 2177.36   385.7 2178.51
   402.5 2178.27   445.7 2174.62   465.7 2169.74   477.7  2172.2   488.9 2172.71
   501.7 2172.42   521.7 2173.41  529.122171.577   533.7 2170.92  543.072171.611
   569.7 2173.85   585.7 2172.58   601.7 2172.79   617.7 2174.26   621.7  2175.9
   629.7 2184.12   653.7 2201.59   685.7  2220.9   689.7 2223.11   695.1  2224.6
#Mann= 3, -1 ,  0
       0     0.1       0  529.12   0.045       0  543.07     0.1       0
#XS Ineff= 2 , 0
                          569.81         2179.17
Permanent Ineff=
       F       F
Bank Sta=529.12,543.07
XS Rating Curve= 0 ,0
Exp/Cntr(USF)=0,0
Exp/Cntr=0.3,0.1

Type RM Length L Ch R = 1 ,1355    ,460.8,461.6,458.2
XS GIS Cut Line= 3
 2303796.4234842661478.5261719482303434.18143361661965.372367702
2303420.83098949662025.894381068
#Sta/Elev= 30
       0 2183.99    43.2  2182.5    93.6  2179.4   167.8 2172.22   239.3 2169.95
   270.8 2167.74   302.2 2168.71   322.4  2167.7   347.3 2167.94     369 2165.19
   382.4 2161.93   402.2 2163.19   439.5 2162.48   453.8 2159.36   470.9 2161.98
  481.372159.688   496.6 2159.25   498.7 2159.67   506.9 2161.15   523.1 2161.85
   546.8 2161.95   556.7 2159.65   571.7 2160.43   576.7 2162.53   585.3 2170.53
   599.5 2181.05   621.8 2195.45   651.7  2208.9   659.9 2209.82   668.8 2213.87
#Mann= 3, -1 ,  0
       0     0.1       0  481.37   0.045       0   498.7     0.1       0
#XS Ineff= 2 , 0
                          512.44         2167.68
Permanent Ineff=
       F       F
Bank Sta=481.37,498.7
XS Rating Curve= 0 ,0
Exp/Cntr(USF)=0,0
Exp/Cntr=0.3,0.1

Type RM Length L Ch R = 1 ,894     ,277.2,274.1,272.8
XS GIS Cut Line= 2
2303435.58752019661300.6636251522303086.69591373661850.701923097
#Sta/Elev= 30
       0 2192.65    43.4  2185.7   121.7 2175.63   180.6 2170.59   199.6 2170.07
   242.2 2164.22   261.1 2160.93   265.9 2159.24   272.4 2154.06   280.1  2145.9
     284 2143.61   289.6 2143.14   310.1  2143.7   318.8 2145.07   327.5 2148.47
     335  2149.5   384.3 2149.65   439.5  2147.6   461.9  2150.5   472.4 2149.53
   491.8 2150.03   502.7 2149.34   524.6 2150.31   547.6 2149.94   559.3 2150.86
     568 2148.13   573.8 2148.31   588.9 2155.17     626 2174.87   651.4  2184.9
#Mann= 6, -1 ,  0
       0     0.1       0     284   0.045       0   310.1     0.1       0
     450    0.05       0     510     0.1       0     630    0.06       0
Bank Sta=284,310.1
XS Rating Curve= 0 ,0
Exp/Cntr(USF)=0,0
Exp/Cntr=0.3,0.1

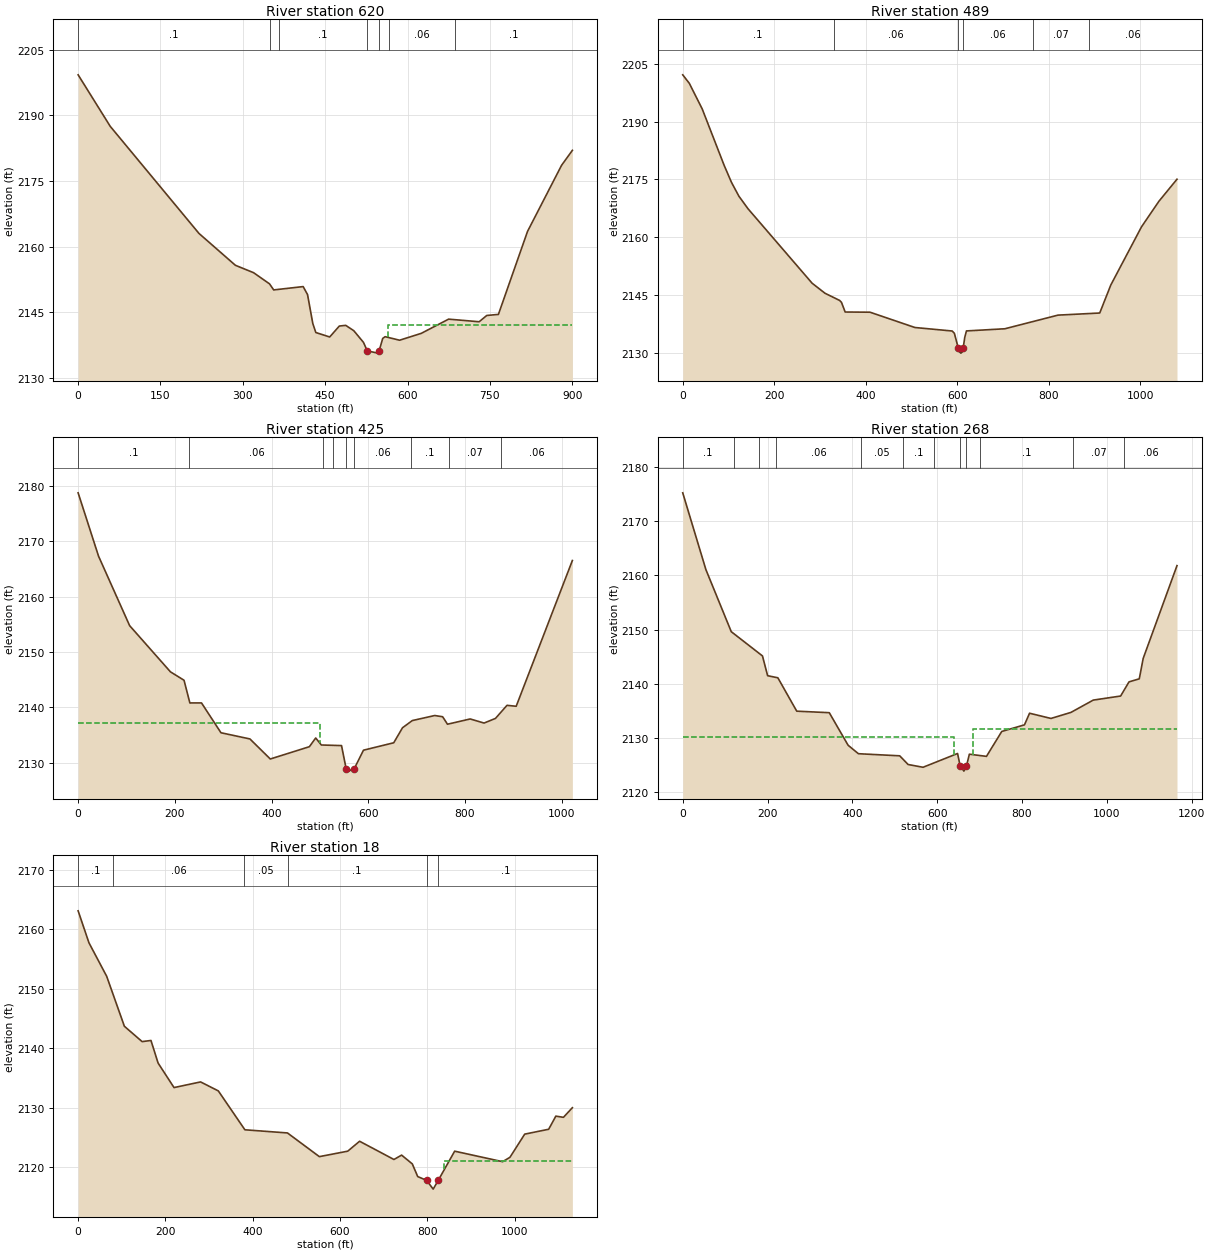
Type RM Length L Ch R = 1 ,620     ,127.7,131.2,133.9
XS GIS Cut Line= 4
2303428.70169441661235.6951264182303084.78766095661328.289338407
 2302908.6020879661717.947108981 2302958.6586228661822.943743159
#Sta/Elev= 30
       0 2199.27    58.5 2187.49   220.1 2163.01   286.4 2155.73   319.5 2154.04
   348.5 2151.49   356.2  2150.1   409.8 2150.86   417.8 2149.04   427.4 2142.41
   432.9 2140.36   458.1 2139.34   475.7 2141.84   487.3    2142     502 2140.78
   519.6 2138.12   526.6 2136.16   545.9 2135.65548.1093 2136.15   554.7 2139.01
   559.1 2139.41   585.4  2138.6   624.9 2140.17   674.7 2143.42   730.3 2142.82
   744.2 2144.26   765.4  2144.5   818.4 2163.47   880.4 2178.58   900.1 2182.01
#Mann= 7, -1 ,  0
       0     0.1       0     350    0.06       0  366.16     0.1       0
   526.6   0.045       0548.1093     0.1       0  566.16    0.06       0
  686.16     0.1       0
#XS Ineff= 2 , 0
                           563.6         2142.14
Permanent Ineff=
       F       F
Bank Sta=526.6,548.1093
XS Rating Curve= 0 ,0
Exp/Cntr(USF)=0,0
Exp/Cntr=0.3,0.1

Type RM Length L Ch R = 1 ,489     ,64.7,63.2,62.4
XS GIS Cut Line= 6
2303422.59723894661188.0803737092303062.43436588661210.056413421
2302956.21684061661357.7842359272302830.46505782661504.291167339
2302757.21159211661625.1593857542302871.97535505661792.421465782
#Sta/Elev= 30
       0 2202.12    14.4 2199.91    42.5 2193.29    90.6 2178.61   106.6 2174.21
   122.7 2170.64   142.7 2167.37   282.9 2148.04     311 2145.44   343.1 2143.57
   347.1 2143.07   355.1 2140.57   409.4 2140.52   507.6 2136.55   589.1 2135.64
   593.9 2135.04   602.4 2131.24   604.7 2130.26   608.1  2129.9   610.9 2130.18
  613.212131.279   616.6 2133.99   620.3 2135.66   704.2 2136.22   820.4 2139.76
   911.7 2140.31   935.9 2147.58  1003.1 2162.69    1041 2169.29  1080.6 2175.03
#Mann= 6, -1 ,  0
       0     0.1       0     330    0.06       0   602.4   0.045       0
  613.21    0.06       0  766.34    0.07       0  887.71    0.06       0
Bank Sta=602.4,613.21
XS Rating Curve= 0 ,0
Exp/Cntr(USF)=0,0
Exp/Cntr=0.3,0.1

Type RM Length L Ch R = 1 ,425     ,158.4,157.4,156.6
XS GIS Cut Line= 4
2303326.14684243661141.6865120952302990.40179127661174.650571663
2302721.80575035661593.4162172812302823.13971125661750.911168549
#Sta/Elev= 30
       0 2178.76    42.2 2167.33   106.5 2154.78   190.9 2146.44     219 2144.92
   231.1 2140.82   255.2 2140.82   295.4 2135.44   355.3 2134.32   397.4  2130.7
   478.2 2132.92   491.3 2134.49   502.9 2133.23   544.7 2133.12   554.2 2128.97
     559 2128.51   571.2 2128.98   590.1 2132.29   652.7 2133.63   670.8 2136.34
   691.1 2137.64   737.4 2138.55   753.8 2138.33   763.8 2136.98   810.8 2137.93
   839.5 2137.19   863.1 2138.03   886.9 2140.39   905.9 2140.22  1022.1 2166.54
#Mann= 9, -1 ,  0
       0     0.1       0     230    0.06       0  507.36     0.1       0
  527.36    0.06       0   554.2   0.045       0   571.2    0.06       0
  687.36     0.1       0  767.36    0.07       0  874.86    0.06       0
#XS Ineff= 2 , 0
          499.94 2137.11
Permanent Ineff=
       F       F
Bank Sta=554.2,571.2
XS Rating Curve= 0 ,0
Exp/Cntr(USF)=0,0
Exp/Cntr=0.3,0.1

Type RM Length L Ch R = 1 ,268     ,240.8,249.6,260.3
XS GIS Cut Line= 4
2303310.27525819661109.943343623 2302784.0711962661184.417700424
2302640.00604698661468.8853255812302796.28010715661742.364930883
#Sta/Elev= 30
       0 2175.19    54.6 2161.04   114.4  2149.6     188 2145.13   200.1 2141.49
   224.3  2141.1   268.8 2134.95   345.5 2134.67   389.9 2128.67   414.2 2127.11
   511.6 2126.72   531.4 2125.12   566.6 2124.61     648 2127.15     654 2124.87
   662.9  2123.9   668.9 2124.83   675.8 2127.02   716.1 2126.62   752.2 2131.21
   805.7 2132.43   817.7 2134.57   868.2 2133.61   915.2 2134.72   967.9 2136.99
  1032.4 2137.74  1052.2 2140.35  1076.4 2140.91  1085.6 2144.67  1165.3 2161.77
#Mann= 12, -1 ,  0
       0     0.1       0     120    0.06       0     180     0.1       0
     220    0.06       0     420    0.05       0     520     0.1       0
  591.45    0.06       0     654   0.045       0   668.9    0.06       0
  701.45     0.1       0  920.32    0.07       0 1040.32    0.06       0
#XS Ineff= 2 ,-1
       0  639.68  2130.1  684.451165.296 2131.61
Permanent Ineff=
       F       F
Bank Sta=654,668.9
XS Rating Curve= 0 ,0
Exp/Cntr(USF)=0,0
Exp/Cntr=0.3,0.1

Type RM Length L Ch R = 1 ,18      ,,,
XS GIS Cut Line= 6
2303272.61919852661078.0086108692302664.61543316661184.226136143
2302602.34998731 661217.190195712302520.73400396661240.068388611
2302459.14597936661268.5813727462302552.71044654661544.622644487
#Sta/Elev= 30
       0 2163.14    24.8 2157.76    65.4 2152.12     106  2143.7   146.6 2141.12
   166.9 2141.31   183.2 2137.51   219.7 2133.38   280.6 2134.33   321.2 2132.82
   382.1 2126.27   479.6 2125.74   552.7 2121.75   617.7 2122.67   644.9 2124.34
   723.6 2121.27   741.1 2122.01   765.6 2120.53   778.1 2118.39   798.4 2117.76
   813.5 2116.28  825.212117.781   862.7 2122.67   972.5  2120.9   989.4 2121.64
  1023.2 2125.54  1078.1 2126.36  1094.5 2128.57  1111.9 2128.37  1132.4 2129.99
#Mann= 6, -1 ,  0
       0     0.1       0      80    0.06       0     380    0.05       0
     480     0.1       0   798.4   0.045       0  825.21     0.1       0
#XS Ineff= 2 , 0
                          839.13         2120.96
Permanent Ineff=
       F       F
Bank Sta=798.4,825.21
XS Rating Curve= 0 ,0
Exp/Cntr(USF)=0,0
Exp/Cntr=0.3,0.1
LCMann Table=0

Chan Stop Cuts=-1
Use User Specified Reach Order=0
Composite Channel Slope=5